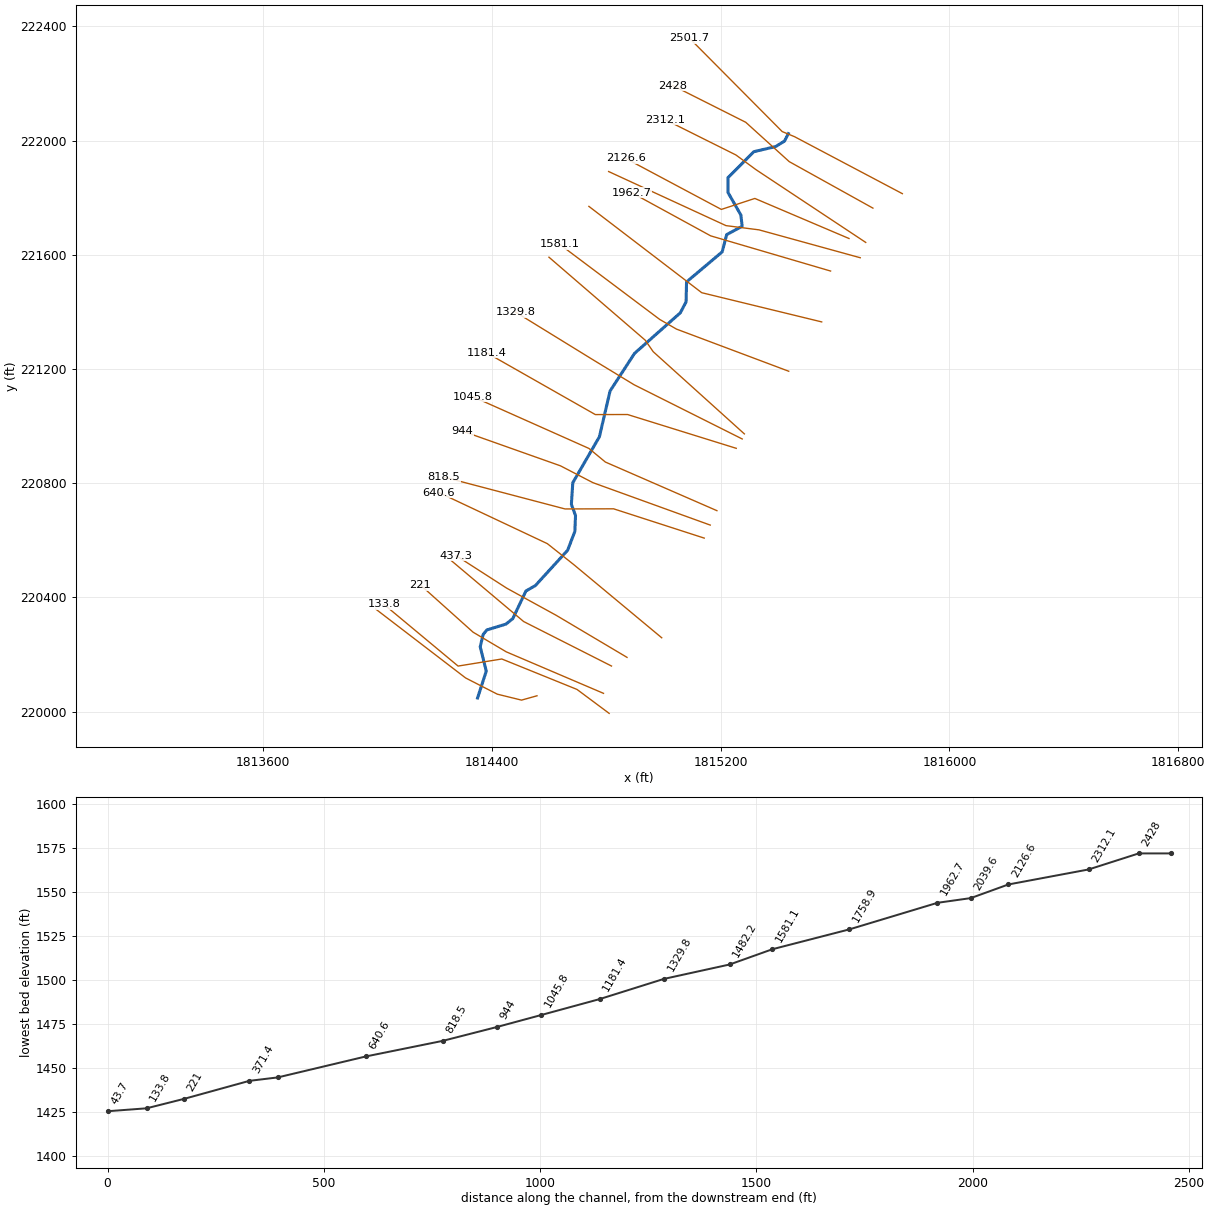
--- GulfBr.prj (project) ---

Proj Title=GulfBr
Current Plan=p01
Default Exp/Contr=0,0
English Units
Geom File=g01
Flow File=f01
Plan File=p01
BEGIN DESCRIPTION:
END DESCRIPTION:
DSS Export Rating Curves= 0
DSS Export Rating Curve Sorted= 0
DSS Export Volume Flow Curves= 0
DXF OffsetX= 0
DXF OffsetY= 0
DXF ScaleX= 0
DXF ScaleY= 0

--- GulfBr.p01 (plan) ---

Plan Title=Floodplain
Program Version=4.00
Geom File=g01
Flow File=f01
K Sum by GR=0
Std Step Tol=0.01
Critical Tol=0.01
Num of Std Step Trials=20
Max Error Tol=0.3
Flow Tol Ratio=0.001
Split Flow NTrial=30
Split Flow Tol=0.02
Split Flow Ratio=0.02
Log Output Level=0
Friction Slope Method=1
Unsteady Friction Slope Method=2
Unsteady Bridges Friction Slope Method=1
Global Log Level=0
CheckData=False
Run HTab=0
Run UNet=0
Run PostProcess=0
UNET Theta=0
UNET Theta Warmup=0
UNET ZTol=0
UNET ZSATol=0
UNET MxIter=0
UNET MaxInSteps=0
UNET DtIC=0
UNET DtMin=0
UNET MaxCRTS=0
UNET WFStab=0
UNET SFStab=0
UNET WFX=0
UNET SFX=0
UNET DSS MLevel=0
UNET DZMax Abort=0
UNET Convert EG Bridges=0
UNET Use Existing IB Tables=0
UNET Froude Limit=0
UNET Froude Power=0
Write IC File=0
Echo Input=False
Echo Output=False
Write Detailed=0

--- GulfBr.f01 (steady flow) ---

Flow Title=NFF Regression Equation
Program Version=4.00
Number of Profiles=1
Profile Names=P100yr
River Rch & RM=GulfBr,Main      ,2501.7
572.5939
River Rch & RM=GulfBr,Main      ,1482.2
618.1558
River Rch & RM=GulfBr,Main      ,221
632.0976
Boundary for River Rch & Prof#=GulfBr,Main      ,1
Up Type=0
Dn Type=3
Dn Slope=0.050033

--- GulfBr.g01 (geometry) ---

Geom Title=USGS 10m DEM
Program Version=4.00

River Reach=GulfBr          ,Main
Reach XY= 30
     1815436.493      222024.031       1815423.3      221998.034
     1815391.871      221978.633     1815315.819      221960.784
     1815225.444      221869.908     1815225.444      221818.068
     1815270.523      221739.181      1815275.03      221699.737
     1815220.936      221670.437     1815205.137      221610.012
     1815080.552      221504.799      1815078.94      221434.903
     1815058.655      221396.586     1814898.627       221254.59
     1814813.079      221122.991     1814775.789      220962.708
     1814682.706      220801.713     1814677.744      220726.047
     1814692.227      220686.939     1814689.948      220631.503
     1814664.598      220565.282     1814551.814      220441.634
     1814518.704      220422.491     1814472.659      220325.746
     1814448.711      220306.648     1814381.987      220286.299
     1814369.188      220270.389     1814358.841      220227.448
     1814380.052      220142.085     1814349.616      220047.936

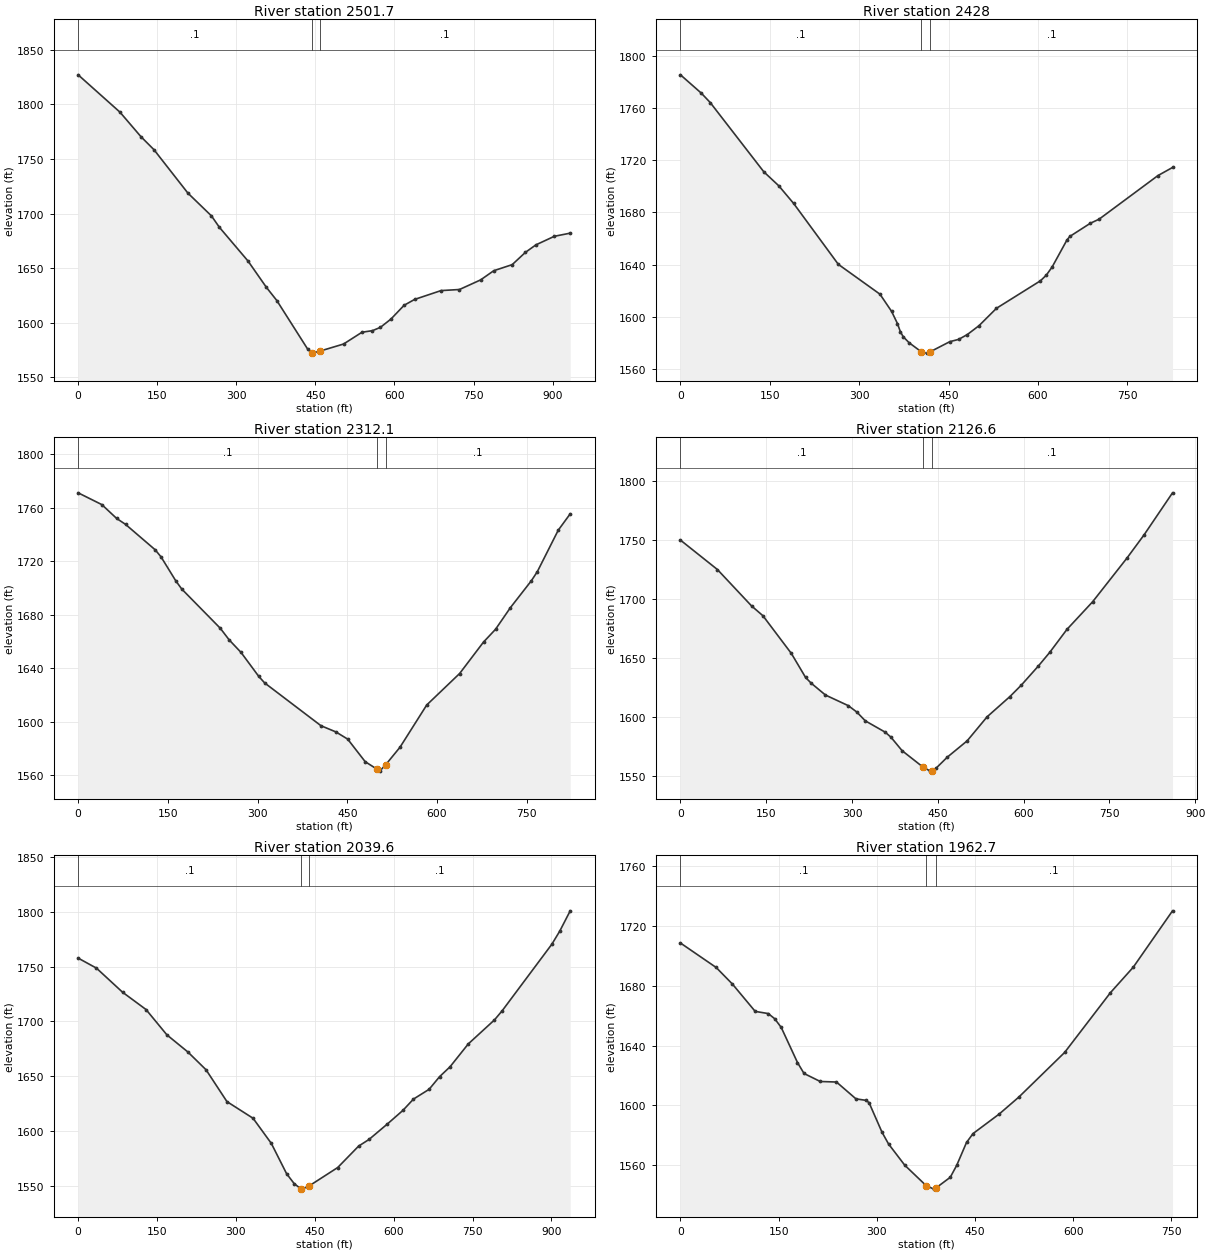
Type RM Length L Ch R = 1 ,2501.7  ,79.6,73.6,68.9
XS GIS Cut Line= 4
     1815835.401      221813.892     1815458.475      222013.289
     1815415.117      222031.281     1815091.187      222357.745
#Sta/Elev= 30
       0 1827.19    79.3 1792.99     119 1770.58   143.8 1758.58   208.2 1718.79
   252.9 1697.89   267.8 1687.53   322.3  1656.5     357 1632.48   376.8 1620.37
   435.8 1575.49   443.5  1572.4   445.2 1572.15   458.5 1573.98   503.4 1580.49
   538.4 1591.29   558.3 1592.75   573.3 1595.77   593.3 1603.37   618.3 1616.01
   638.3 1621.39   688.3 1629.46   723.3 1630.45   763.3 1639.24   788.3 1647.67
   823.3 1653.25   848.3 1664.48   868.3 1671.38   903.3 1679.23   933.3  1682.1
#Mann= 3 , 0 , 0
       0      .1       0   443.5    .045       0   458.5      .1       0
Bank Sta=443.5,458.5
XS Rating Curve= 0 ,0
Exp/Cntr=0.3,0.1

Type RM Length L Ch R = 1 ,2428    ,115.5,115.9,115.6
XS GIS Cut Line= 4
     1815732.436      221763.229     1815439.733      221926.031
      1815287.57      222063.853     1815032.311      222192.398
#Sta/Elev= 30
       0 1785.43      35 1771.39      50 1764.17     140 1711.06     165 1700.41
     190 1686.85     265 1640.18   334.9 1617.31   354.5 1604.08   364.3 1594.75
   369.2 1588.48     374 1584.68   383.8 1580.11   404.1 1573.24   413.1 1572.14
   419.1 1573.14   452.2 1580.94   466.9 1582.65   481.6 1586.39   501.1 1593.15
   530.5 1606.51   604.3 1627.58   614.2 1631.94     624 1638.22   648.6 1658.69
   653.6 1661.57   688.1 1671.68   702.8 1674.81   801.4 1708.18     826 1714.42
#Mann= 3 , 0 , 0
       0      .1       0   404.1    .045       0   419.1      .1       0
Bank Sta=404.1,419.1
XS Rating Curve= 0 ,0
Exp/Cntr=0.3,0.1

Type RM Length L Ch R = 1 ,2312.1  ,164.1,185.6,206.5
XS GIS Cut Line= 4
     1815707.291      221643.165     1815323.498      221897.832
      1815253.08      221949.458     1815007.166      222072.333
#Sta/Elev= 30
       0 1771.24    39.6 1762.43    64.4 1752.07    79.2 1747.66   128.8 1728.62
   138.7 1723.26   163.4  1705.3   173.3 1699.23   237.7 1669.89   252.6 1661.18
   272.4 1651.82   302.1 1633.84     312 1628.96   406.1 1596.97   430.9 1592.37
   450.7 1586.97     480 1570.07   499.5 1564.55   504.3 1563.01   514.5 1567.93
   538.2 1580.89   582.9  1612.5   637.9 1636.04   677.9 1659.61   697.9 1669.11
   722.8 1685.32   757.8 1705.42   767.8 1712.23   802.8 1743.27   822.8 1755.51
#Mann= 3 , 0 , 0
       0      .1       0   499.5    .045       0   514.5      .1       0
Bank Sta=499.5,514.5
XS Rating Curve= 0 ,0
Exp/Cntr=0.3,0.1

Type RM Length L Ch R = 1 ,2126.6  ,95.8,86.9,81.4
XS GIS Cut Line= 4
     1815648.812      221656.867     1815319.399      221797.153
     1815202.251      221758.736     1814867.849      221937.175
#Sta/Elev= 30
       0 1749.71    64.6 1724.85   124.3 1694.09   144.2 1685.78   193.9 1653.92
   218.8 1633.62   228.8  1628.7   253.6 1618.75   293.4 1609.81   308.3 1604.43
   323.2 1596.96     358 1587.38   367.9 1583.22   387.6 1571.72   424.3  1557.8
   436.9 1554.46   439.3 1554.78   446.8 1556.87   466.5 1566.22   501.3 1580.05
   536.2 1600.37   576.1 1617.48     596 1627.13     626  1643.4   645.9 1654.94
   675.8 1674.25   720.7 1697.59   780.6 1734.44   810.5 1754.04   860.4 1789.67
#Mann= 3 , 0 , 0
       0      .1       0   424.3    .045       0   439.3      .1       0
Bank Sta=424.3,439.3
XS Rating Curve= 0 ,0
Exp/Cntr=0.3,0.1

Type RM Length L Ch R = 1 ,2039.6  ,89.8,76.9,69.1
XS GIS Cut Line= 4
     1815688.134      221589.503     1815333.938      221687.164
     1815218.568      221701.955     1814808.123      221891.317
#Sta/Elev= 30
       0 1757.92    34.8 1748.75    84.4 1726.76   129.1  1710.9   168.8 1687.73
   208.5 1672.17   243.3 1655.79     283 1626.72   332.7 1611.47   367.4  1588.5
   396.5 1560.74     411 1551.66   423.8 1546.93   425.6  1546.7   438.8 1549.47
   493.7 1566.46   533.4 1586.03   553.3 1592.15     588 1606.21   617.8 1618.76
   637.7 1629.01   667.5 1637.97   687.4 1649.53   707.2  1658.5     742 1679.48
   791.7 1701.37   806.6 1709.87     901 1770.68   915.9 1782.55   935.8 1801.14
#Mann= 3 , 0 , 0
       0      .1       0   423.8    .045       0   438.8      .1       0
Bank Sta=423.8,438.8
XS Rating Curve= 0 ,0
Exp/Cntr=0.3,0.1

Type RM Length L Ch R = 1 ,1962.7  ,212.4,203.8,195.2
XS GIS Cut Line= 3
     1815584.356      221542.945     1815164.961      221666.164
     1814888.834      221817.257
#Sta/Elev= 30
       0 1708.49    54.6 1692.13    79.5 1681.01   114.2  1662.8   134.1 1661.35
     144  1657.9     154 1652.06   178.8 1628.64   188.8 1621.31   213.6 1615.96
   238.4  1615.6   268.2 1604.34   283.1 1603.38   288.1 1601.89     308 1582.04
   317.9 1574.26   342.7 1560.04   375.4 1546.38   387.4 1544.03   390.4 1544.79
   412.3 1551.95   422.2 1559.99   437.1 1575.19   447.1 1581.16   487.1 1594.22
   517.1 1605.55     587 1635.34     657 1675.29   691.9 1692.32   751.9    1730
#Mann= 3 , 0 , 0
       0      .1       0   375.4    .045       0   390.4      .1       0
Bank Sta=375.4,390.4
XS Rating Curve= 0 ,0
Exp/Cntr=0.3,0.1

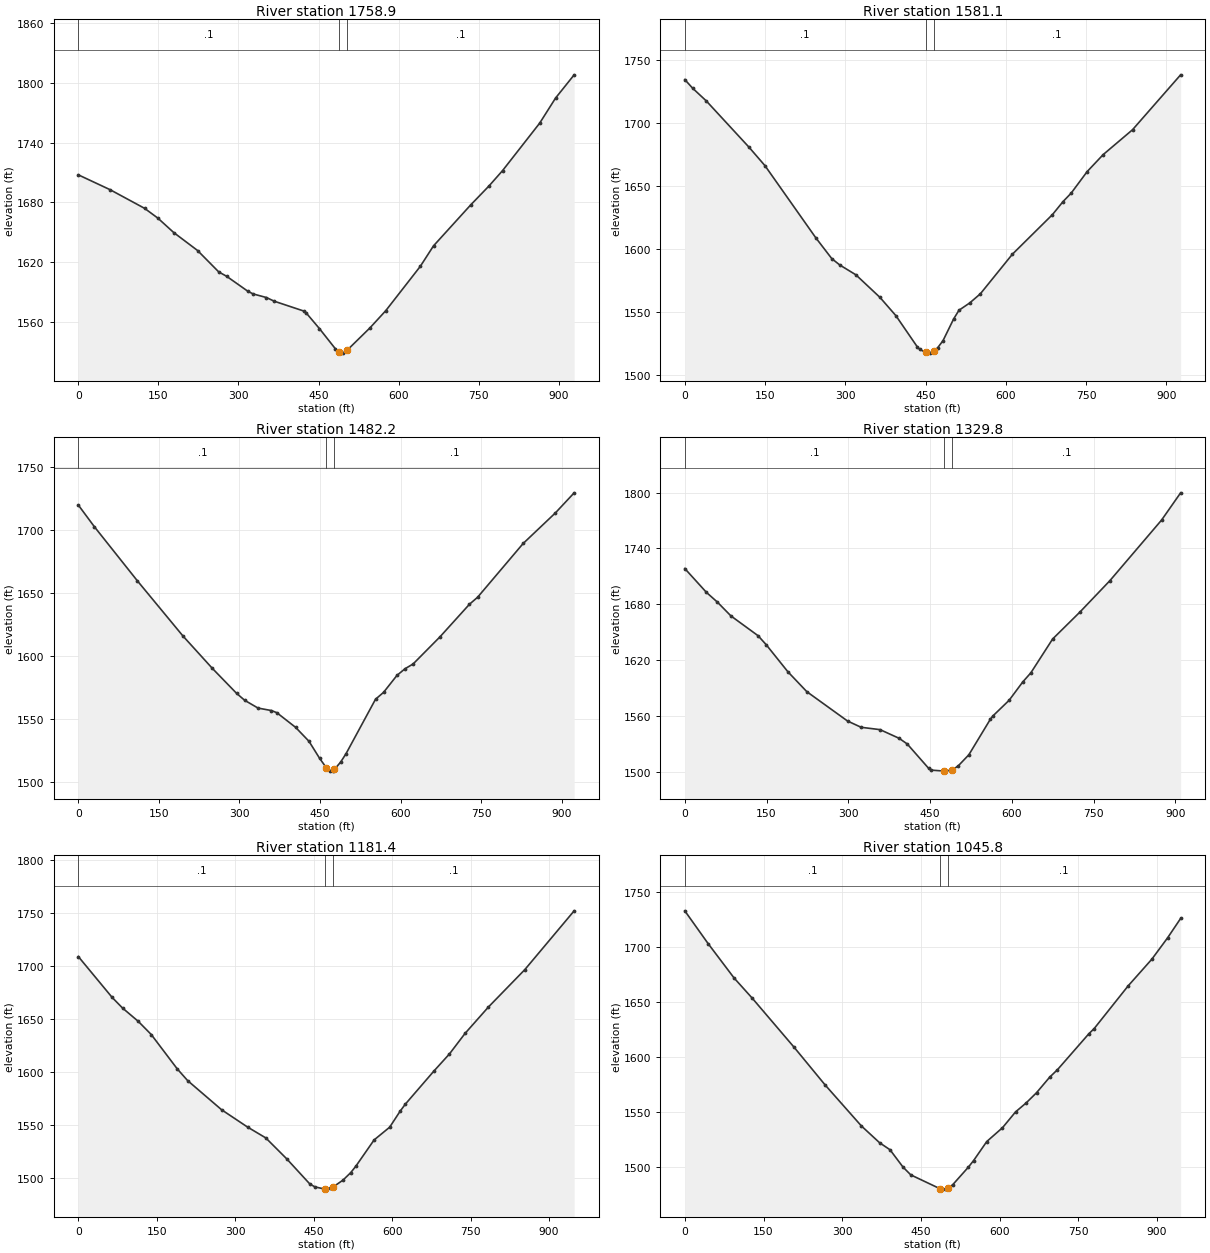
Type RM Length L Ch R = 1 ,1758.9  ,174.9,177.8,180.6
XS GIS Cut Line= 3
     1815553.294      221364.847     1815133.704      221467.088
     1814738.972      221769.354
#Sta/Elev= 30
       0 1707.66    59.6 1692.75   124.1 1674.09   148.9 1664.32   178.7 1649.82
   223.4  1631.8   263.1 1610.32     278 1605.89   317.7 1590.91   327.6 1588.24
   352.4 1584.65   367.3 1580.91   421.9 1571.19   426.9 1569.23   451.8 1553.46
   481.6 1533.26   489.1 1529.93   491.5  1528.9   496.5 1529.08   504.1 1532.06
   546.2 1554.11     576 1571.45   640.7 1615.88   665.5 1636.48   735.1 1677.48
   769.9 1696.78   794.8 1711.88   864.4  1759.5   894.2 1784.68     929 1807.95
#Mann= 3 , 0 , 0
       0      .1       0   489.1    .045       0   504.1      .1       0
Bank Sta=489.1,504.1
XS Rating Curve= 0 ,0
Exp/Cntr=0.3,0.1

Type RM Length L Ch R = 1 ,1581.1  ,108.8,98.8,92.3
XS GIS Cut Line= 4
     1815438.003      221192.078     1815045.315      221339.676
     1814986.566      221373.601     1814635.561      221637.446
#Sta/Elev= 30
       0 1734.58      15 1727.59      40 1717.73   119.9 1680.99   149.8 1666.31
   244.7 1609.14   274.7 1592.55   289.7 1587.49   319.6 1579.76   364.6 1561.86
   394.5  1547.3     434 1522.85   438.9 1520.59   450.1 1518.19   458.3 1517.61
   465.1 1518.98   472.8 1522.03   482.5  1527.5   502.3 1544.68   512.3 1551.61
   532.3 1557.38   552.2 1564.62   612.1 1596.05     687 1627.49   706.9 1637.88
   721.9 1644.48   751.8 1661.58   781.8 1675.09   836.6 1694.79   926.5 1738.36
#Mann= 3 , 0 , 0
       0      .1       0   450.1    .045       0   465.1      .1       0
Bank Sta=450.1,465.1
XS Rating Curve= 0 ,0
Exp/Cntr=0.3,0.1

Type RM Length L Ch R = 1 ,1482.2  ,142.9,152.4,158.4
XS GIS Cut Line= 4
     1815282.792      220972.742     1814963.927       221260.55
     1814936.091      221300.785     1814599.348      221591.394
#Sta/Elev= 30
       0 1719.84      30  1702.6   109.9  1659.8   194.8 1616.05   249.7 1590.31
   294.7 1570.58   309.7 1565.09   334.6 1558.91   359.6 1556.94   369.6 1555.25
   404.6 1543.62   429.5 1532.58   449.1  1519.2     462 1511.48   468.7 1508.96
   473.6 1508.92     477 1510.36   488.5  1516.1   498.5 1522.75   553.4  1565.9
   568.4 1571.37   593.4 1584.84   608.4  1590.1   623.4 1593.87   673.4 1615.36
   728.4 1641.24   743.4 1646.72   828.3 1689.37   888.3 1713.59   923.3 1729.54
#Mann= 3 , 0 , 0
       0      .1       0     462    .045       0     477      .1       0
Bank Sta=462,477
XS Rating Curve= 0 ,0
Exp/Cntr=0.3,0.1

Type RM Length L Ch R = 1 ,1329.8  ,136.1,148.5,160.9
XS GIS Cut Line= 4
     1815275.253      220954.983     1814897.198      221144.746
     1814754.509      221231.536     1814482.369      221399.234
#Sta/Elev= 30
       0 1718.42    39.8 1692.73    59.7 1682.39    84.6 1667.51   134.4 1646.24
   149.3 1636.61   189.1  1607.5   223.9 1586.07   298.6 1554.54   323.5 1547.81
   358.3 1545.27   393.2 1535.98   408.1 1529.89   447.6 1503.55   452.5 1501.77
   475.8 1500.73     477 1500.69   490.8    1502   501.6  1506.3   521.2 1518.29
   560.6 1556.44   565.5 1560.13     595  1576.8     620 1596.49     635 1606.42
   674.9 1642.72   724.9 1671.62   779.8 1705.31   874.7 1770.48   909.7 1799.79
#Mann= 3 , 0 , 0
       0      .1       0   475.8    .045       0   490.8      .1       0
Bank Sta=475.8,490.8
XS Rating Curve= 0 ,0
Exp/Cntr=0.3,0.1

Type RM Length L Ch R = 1 ,1181.4  ,151.2,135.5,124
XS GIS Cut Line= 4
     1815254.405      220922.214     1814874.212      221040.572
      1814761.54      221040.379     1814381.587      221256.588
#Sta/Elev= 30
       0 1709.08    64.7 1670.41    84.6 1660.37   114.5 1647.87   139.4 1635.38
   189.1  1602.9     209  1591.8   273.8 1564.29   323.5 1547.89   358.4 1537.63
   398.2 1517.96   442.3 1494.23   452.1 1491.35   471.7  1489.2   472.4 1489.22
   481.5 1489.95   487.4 1491.35     506 1497.71   520.8 1504.78   530.7 1510.95
   565.5  1535.7   595.3 1547.77   615.2 1562.84   625.1 1569.48   679.8  1600.8
   709.6 1617.04   739.4 1636.42   784.1 1661.39   853.6 1696.69     948 1752.32
#Mann= 3 , 0 , 0
       0      .1       0   472.4    .045       0   487.4      .1       0
Bank Sta=472.4,487.4
XS Rating Curve= 0 ,0
Exp/Cntr=0.3,0.1

Type RM Length L Ch R = 1 ,1045.8  ,96.8,101.9,102.7
XS GIS Cut Line= 4
     1815186.771      220703.948     1814796.672      220874.159
     1814738.993      220921.875     1814333.256      221102.924
#Sta/Elev= 30
       0 1733.16    44.5 1703.31      94 1672.04   128.7 1653.63   207.9 1609.32
   267.2 1574.94   336.5 1537.55   371.2 1522.28     391 1515.92   415.7 1500.22
   430.6 1493.07   485.8  1480.6   495.5 1480.11   500.8  1480.7   510.5 1484.11
   540.4 1500.12   550.4 1506.14   575.4 1523.38   605.3 1535.92   630.3 1550.34
   650.2 1558.38   670.2 1567.74   695.2 1581.86   710.1 1588.69     770 1621.42
     780 1626.06   844.9 1664.97   889.9 1689.15   919.8 1708.48   944.8 1726.23
#Mann= 3 , 0 , 0
       0      .1       0   485.8    .045       0   500.8      .1       0
Bank Sta=485.8,500.8
XS Rating Curve= 0 ,0
Exp/Cntr=0.3,0.1

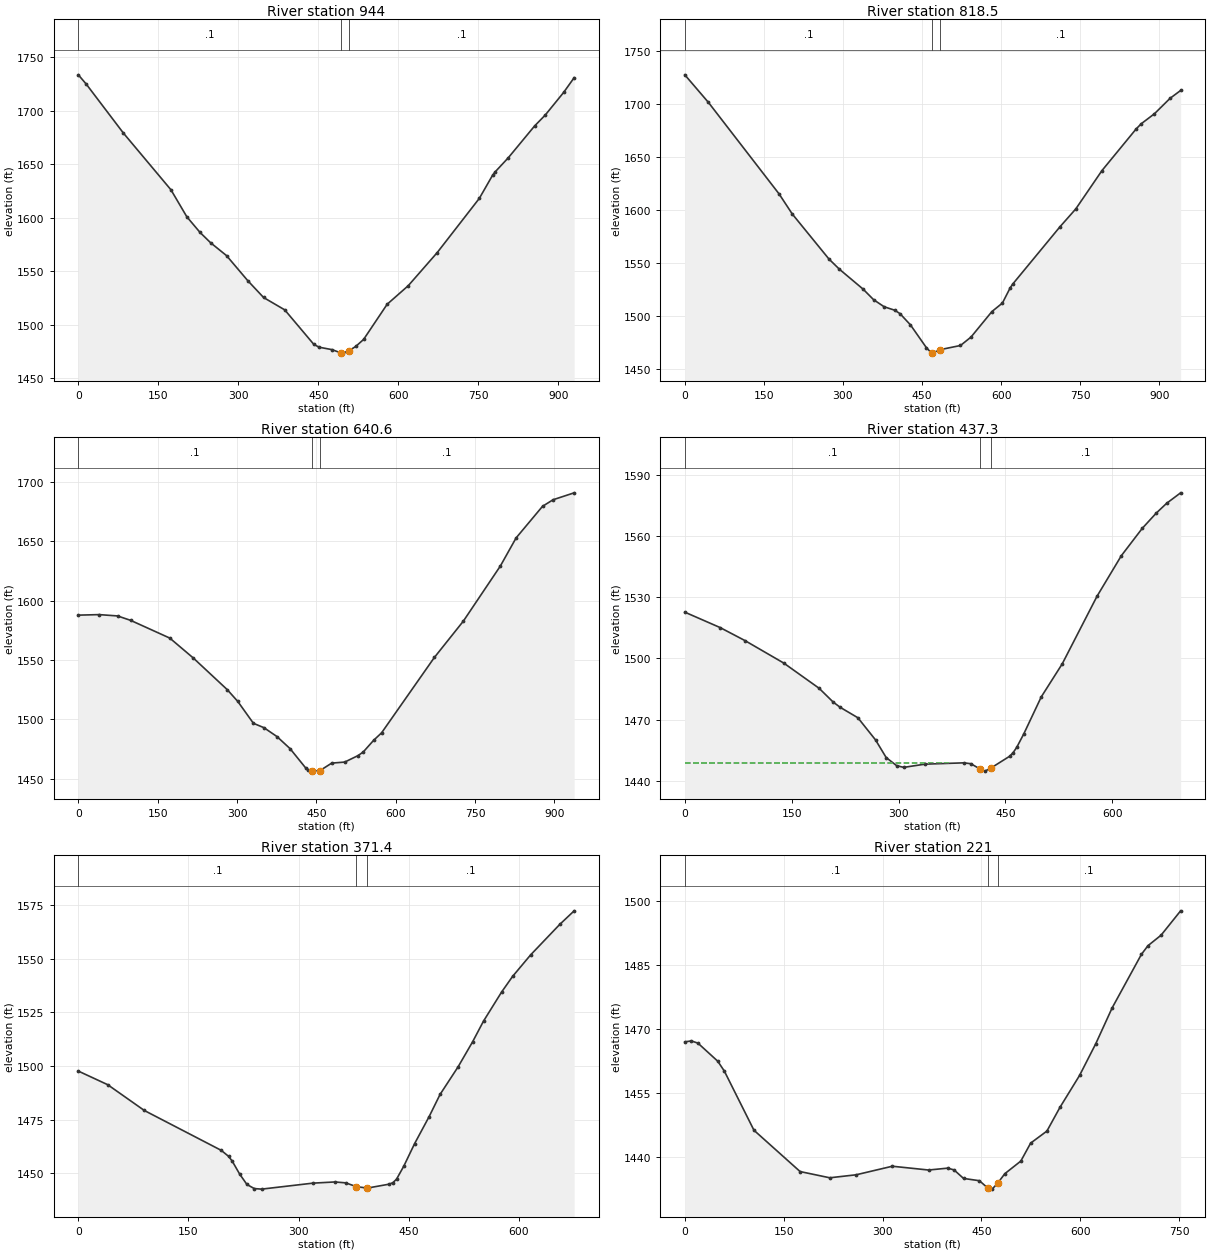
Type RM Length L Ch R = 1 ,944     ,114.8,125.5,136.5
XS GIS Cut Line= 4
     1815163.454      220653.423     1814753.038      220801.996
     1814639.769      220860.837     1814295.548      220982.933
#Sta/Elev= 30
       0  1733.7    14.9 1724.98    84.3 1679.31   173.6 1626.14   203.4 1600.86
   228.2 1586.21     248 1576.57   277.8 1564.55   317.4 1541.23   347.2 1525.38
   386.9 1513.79   441.4 1481.52   451.2 1478.89   475.8 1476.55   492.6 1473.42
   495.4 1473.32   507.6 1475.68   519.9 1479.55   534.7 1486.12   578.9 1519.06
   618.4  1536.4   672.7 1567.38   751.7 1618.15   776.4 1639.68   781.3 1642.89
     806 1656.14   855.3 1685.89   875.1    1696   909.6 1717.18   929.4 1731.03
#Mann= 3 , 0 , 0
       0      .1       0   492.6    .045       0   507.6      .1       0
Bank Sta=492.6,507.6
XS Rating Curve= 0 ,0
Exp/Cntr=0.3,0.1

Type RM Length L Ch R = 1 ,818.5   ,192.9,177.9,162.5
XS GIS Cut Line= 4
     1815142.435      220607.835     1814825.411      220710.413
     1814655.525      220709.948     1814232.453      220821.322
#Sta/Elev= 30
       0 1727.54    44.8 1701.57     179 1615.27   203.9 1596.45   273.5 1554.03
   293.4  1544.4   338.2 1525.72   358.2 1515.73   378.2 1509.08   398.2 1505.84
   408.2 1502.63   428.1 1492.01   458.1 1470.71   468.1 1465.42   469.6 1465.53
   484.6 1468.71     523 1472.61   542.9 1480.53   582.6 1504.57   602.5 1512.56
   617.4 1527.04   622.4 1530.66   711.9 1584.53   741.7 1601.24   791.4 1637.37
   856.1  1676.5     866  1681.5   890.9 1690.87   920.7 1705.46   940.6 1712.81
#Mann= 3 , 0 , 0
       0      .1       0   469.6    .045       0   484.6      .1       0
Bank Sta=469.6,484.6
XS Rating Curve= 0 ,0
Exp/Cntr=0.3,0.1

Type RM Length L Ch R = 1 ,640.6   ,199.2,203.3,207.3
XS GIS Cut Line= 4
     1814993.739      220258.869     1814686.244      220514.928
     1814593.621      220588.468     1814214.733      220767.166
#Sta/Elev= 30
       0 1587.77    39.5 1588.21    74.1  1587.1    98.8 1583.39   172.9 1568.46
   217.4 1551.68   281.6 1525.05   301.4 1515.19     331 1496.76   350.8 1493.11
   375.4 1485.65   400.2 1475.49   429.7 1459.26   434.6 1457.34   441.8  1456.9
   454.4 1456.54   456.8    1457     479 1463.28   503.6 1464.16   528.4 1469.53
   538.4 1472.55   558.3  1482.5   573.3 1488.78     673 1552.14   727.9 1582.78
   797.7 1629.03   827.6 1652.77   877.5 1679.32   897.4 1684.84   937.3 1690.67
#Mann= 3 , 0 , 0
       0      .1       0   441.8    .045       0   456.8      .1       0
Bank Sta=441.8,456.8
XS Rating Curve= 0 ,0
Exp/Cntr=0.3,0.1

Type RM Length L Ch R = 1 ,437.3   ,70.7,65.9,61.1
XS GIS Cut Line= 4
     1814872.433      220190.229     1814625.269      220337.122
     1814451.659      220432.524     1814274.943      220546.306
#Sta/Elev= 30
       0 1522.76    49.6 1515.18    84.3 1508.81   138.8 1497.75   188.4 1485.37
   208.2 1478.58   218.1 1475.98   242.9 1470.86   267.7 1459.95   282.6  1451.3
   297.4 1447.29   307.3 1446.48     337 1448.06   391.5  1448.7   401.4 1448.28
   414.2  1445.7   421.2 1444.63   429.2 1446.06   455.9 1451.95   460.8 1453.74
   465.8 1456.31   475.7 1462.93   500.3 1481.16   529.6 1497.31   578.5 1530.59
   612.7 1550.55     642 1563.96   661.6 1571.44   676.2 1576.26   695.8  1581.4
#Mann= 3 , 0 , 0
       0      .1       0   414.2    .045       0   429.2      .1       0
#XS Ineff= 2 , 0
          370.77 1448.65
Permanent Ineff=
       F       F
Bank Sta=414.2,429.2
XS Rating Curve= 0 ,0
Exp/Cntr=0.3,0.1

Type RM Length L Ch R = 1 ,371.4   ,146.3,150.4,154.5
XS GIS Cut Line= 3
     1814818.029      220159.945     1814510.717      220315.735
     1814257.643      220529.062
#Sta/Elev= 30
       0 1497.64      40  1491.3    89.9 1479.29   194.7 1460.72   204.7 1457.93
   209.7 1455.68   219.7 1449.72   229.7 1444.82   239.7 1442.92   249.7 1442.66
   319.6 1445.45   349.5    1446   364.3 1445.58   378.8 1443.81   393.8 1443.15
   423.6 1444.98   428.5 1445.66   433.5 1447.29   443.4 1453.36   458.2  1463.9
   477.9 1476.42   492.8 1486.76   517.4 1499.63   537.2 1511.31     552 1520.91
   576.7 1534.48   591.6 1541.73   616.2 1551.76   655.8 1565.93   675.5 1572.28
#Mann= 3 , 0 , 0
       0      .1       0   378.8    .045       0   393.8      .1       0
#XS Ineff= 2 , 0
          351.55 1445.73
Permanent Ineff=
       F       F
Bank Sta=378.8,393.8
XS Rating Curve= 0 ,0
Exp/Cntr=0.3,0.1

Type RM Length L Ch R = 1 ,221     ,71.4,87.2,103
XS GIS Cut Line= 4
     1814790.069      220064.314     1814450.013      220209.598
     1814333.898      220278.468     1814149.896      220443.651
#Sta/Elev= 30
       0 1466.98      10  1467.2      20 1466.67      50 1462.44      60 1460.12
   104.9 1446.25   174.9 1436.56   219.9  1435.1   259.8  1435.8   314.8 1437.81
   369.8 1436.92   398.7 1437.36   408.4 1436.95   422.8 1434.95   446.9 1434.41
   459.4 1432.72   466.2 1432.44   474.4  1433.8   485.5 1436.07   509.7 1439.02
   524.6 1443.23   549.3 1446.06   569.1 1451.63   598.8  1459.1   623.5 1466.58
   648.2 1474.94   692.7 1487.52   702.6 1489.54   722.4 1491.99   752.1 1497.71
#Mann= 3 , 0 , 0
       0      .1       0   459.4    .045       0   474.4      .1       0
#XS Ineff= 2 , 0
          319.57 1437.66
Permanent Ineff=
       F       F
Bank Sta=459.4,474.4
XS Rating Curve= 0 ,0
Exp/Cntr=0.3,0.1

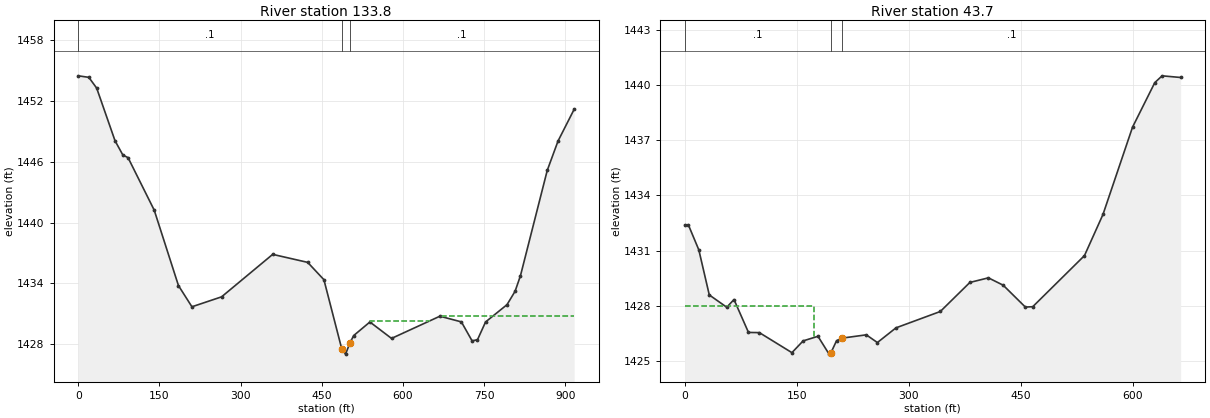
Type RM Length L Ch R = 1 ,133.8   ,104.9,90.1,75.3
XS GIS Cut Line= 5
     1814809.898      219994.157     1814697.365      220078.005
     1814434.468      220184.602     1814281.476      220159.793
     1814022.085      220375.804
#Sta/Elev= 30
       0 1454.48    19.4 1454.33    33.9 1453.27    67.8 1448.08    82.3 1446.67
    91.9 1446.41   140.3 1441.23   185.1 1433.79     210  1431.7   264.8 1432.68
   359.3 1436.87     424 1436.08     454 1434.37   486.8 1427.58     494 1427.03
   501.8  1428.1     509 1428.86     539  1430.2     579 1428.58   668.4 1430.77
   708.1 1430.21   727.9 1428.34   737.9 1428.45   752.8  1430.2   792.5 1431.91
   807.4 1433.23   817.3 1434.76   866.9 1445.16   886.8 1448.05   916.6 1451.18
#Mann= 3 , 0 , 0
       0      .1       0   486.8    .045       0   501.8      .1       0
#XS Ineff= 2 ,-1
  539.42  649.25  1430.3  672.28   916.6 1430.78
Permanent Ineff=
       F       F
Bank Sta=486.8,501.8
XS Rating Curve= 0 ,0
Exp/Cntr=0.3,0.1

Type RM Length L Ch R = 1 ,43.7    ,42.9,43.7,44.5
XS GIS Cut Line= 5
     1814557.515      220055.806     1814503.374      220040.583
     1814418.612      220061.407     1814307.807      220118.145
     1813993.478      220359.339
#Sta/Elev= 30
       0 1432.39     4.7 1432.41    18.8 1431.04    32.8 1428.59    56.2 1427.92
    65.9 1428.34    85.3 1426.55    99.9 1426.54   143.5 1425.45   158.5 1426.09
   178.4 1426.34   193.3 1425.37   195.7 1425.44   203.3  1426.1   210.7 1426.24
   243.1 1426.42     258    1426   282.9  1426.8   342.3 1427.69   381.9 1429.27
   406.7 1429.52   426.5 1429.12   456.2 1427.93   466.1 1427.95   535.4 1430.73
   560.2 1432.97   599.8 1437.72   629.6 1440.14   639.4 1440.51   664.2 1440.42
#Mann= 3 , 0 , 0
       0      .1       0   195.7    .045       0   210.7      .1       0
#XS Ineff= 2 , 0
           173.6 1427.99
Permanent Ineff=
       F       F
Bank Sta=195.7,210.7
XS Rating Curve= 0 ,0
Exp/Cntr=0.3,0.1

Chan Stop Cuts=-1
Use User Specified Reach Order=0